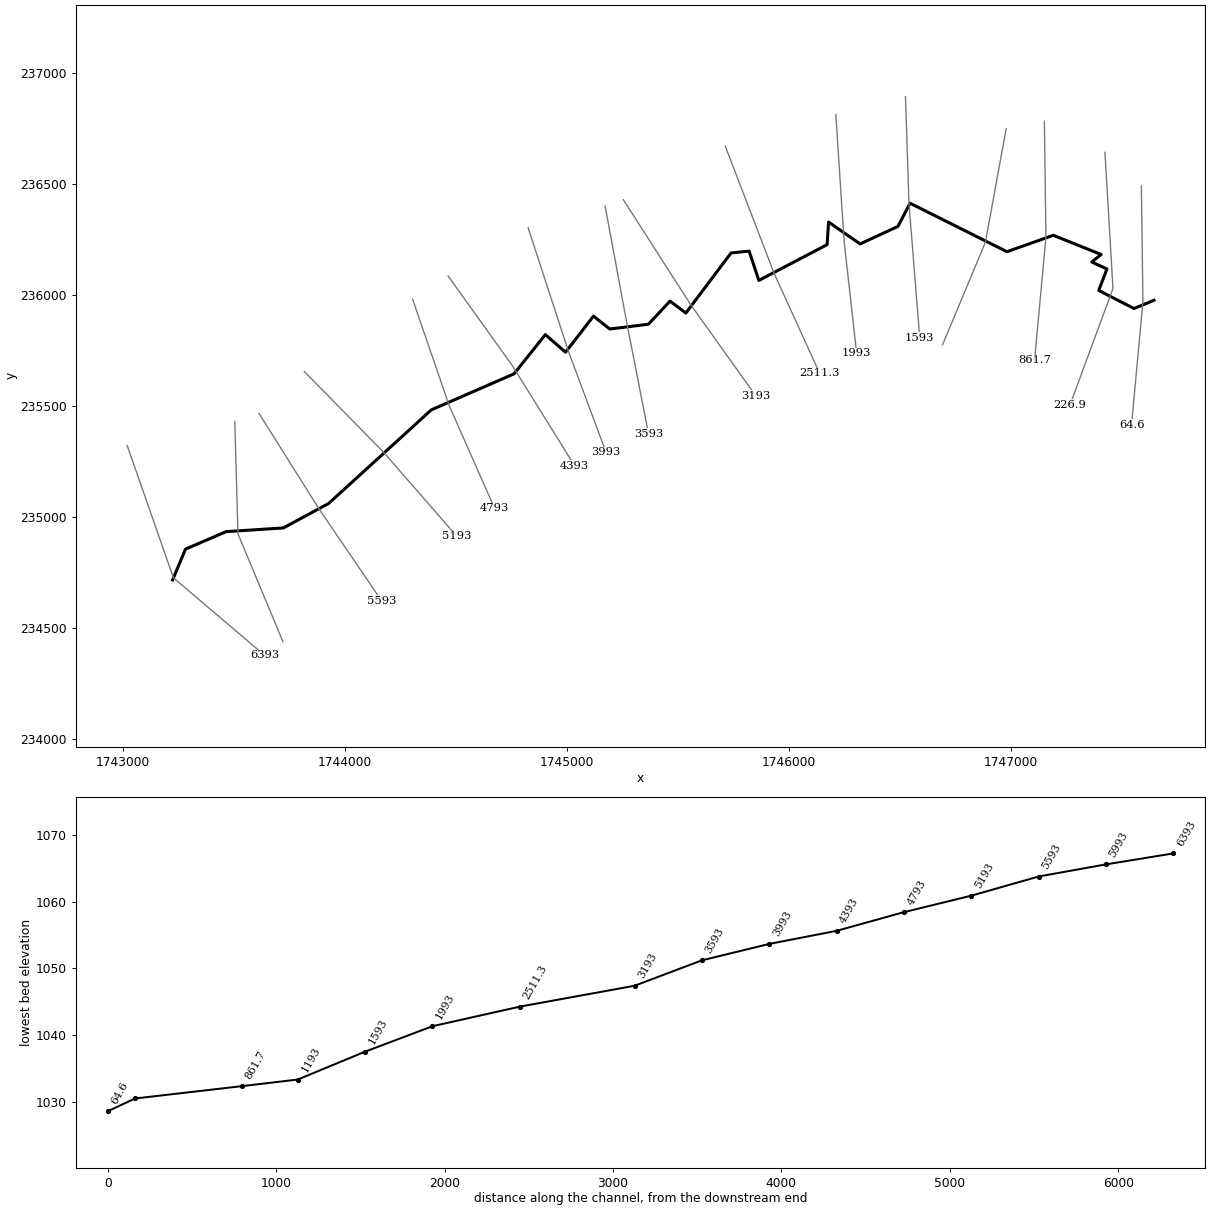
--- RotngCrT2.prj (project) ---

Proj Title=RotngCrT2
Current Plan=p01
Geom File=g01
Flow File=f01
Plan File=p01
DSS Export Rating Curves=0
DSS Export Rating Curve Sorted=0
DSS Export Volume Flow Curves=0
DXF OffsetX=0
DXF OffsetY=0
DXF ScaleX=0
DXF ScaleY=0

--- RotngCrT2.p01 (plan) ---

Plan Title=Floodplain
Program Version=4.00
Geom File=g01
Flow File=f01
K Sum by GR=0
Std Step Tol=0.01
Critical Tol=0.01
Num of Std Step Trials=20
Max Error Tol=0.3
Flow Tol Ratio=0.001
Split Flow NTrial=30
Split Flow Tol=0.02
Split Flow Ratio=0.02
Log Output Level=0
Friction Slope Method=1
Unsteady Friction Slope Method=2
Unsteady Bridges Friction Slope Method=1
Global Log Level=0
CheckData=False
Run HTab=0
Run UNet=0
Run PostProcess=0
UNET Theta=0
UNET Theta Warmup=0
UNET ZTol=0
UNET ZSATol=0
UNET MxIter=0
UNET MaxInSteps=0
UNET DtIC=0
UNET DtMin=0
UNET MaxCRTS=0
UNET WFStab=0
UNET SFStab=0
UNET WFX=0
UNET SFX=0
UNET DSS MLevel=0
UNET DZMax Abort=0
UNET Convert EG Bridges=0
UNET Use Existing IB Tables=0
UNET Froude Limit=0
UNET Froude Power=0
Write IC File=0
Echo Input=False
Echo Output=False
Write Detailed=0

--- RotngCrT2.f01 (steady flow) ---

Flow Title=NFF Regression Equation
Program Version=4.00
Number of Profiles=1
Profile Names=P100yr
River Rch & RM=RotngCrT2,Main      ,6393
759.9212
River Rch & RM=RotngCrT2,Main      ,3593
816.4711
River Rch & RM=RotngCrT2,Main      ,226.9
903.9883
River Rch & RM=RotngCrT2,Main      ,64.6
2357.268
Boundary for River Rch & Prof#=RotngCrT2,Main      ,1
Up Type=0
Dn Type=3
Dn Slope=0.005974

--- RotngCrT2.g01 (geometry) ---

Geom Title=USGS 3m DEM
Program Version=4.00

River Reach=RotngCrT2     ,Main
Reach XY= 30
     1743225.337      234718.322     1743283.065      234857.045
     1743466.452      234935.902     1743723.882      234952.487
     1743927.916      235062.656     1744390.754      235484.462
     1744763.179      235646.659     1744904.297      235823.494
     1744995.397      235744.135     1745121.127      235906.729
     1745194.729      235848.689     1745368.823      235870.349
     1745466.059      235974.387     1745537.434      235920.683
     1745741.049      236191.333     1745822.351      236199.777
     1745866.211      236067.688     1746173.664      236228.673
     1746180.366      236330.612     1746322.406      236231.999
     1746492.919      236310.996     1746547.516      236415.282
     1746983.973      236197.017     1747192.862      236270.906
     1747408.433      236184.398     1747366.017      236150.681
     1747434.347      236119.255     1747397.442      236022.563
     1747556.385      235940.945     1747646.717      235978.430

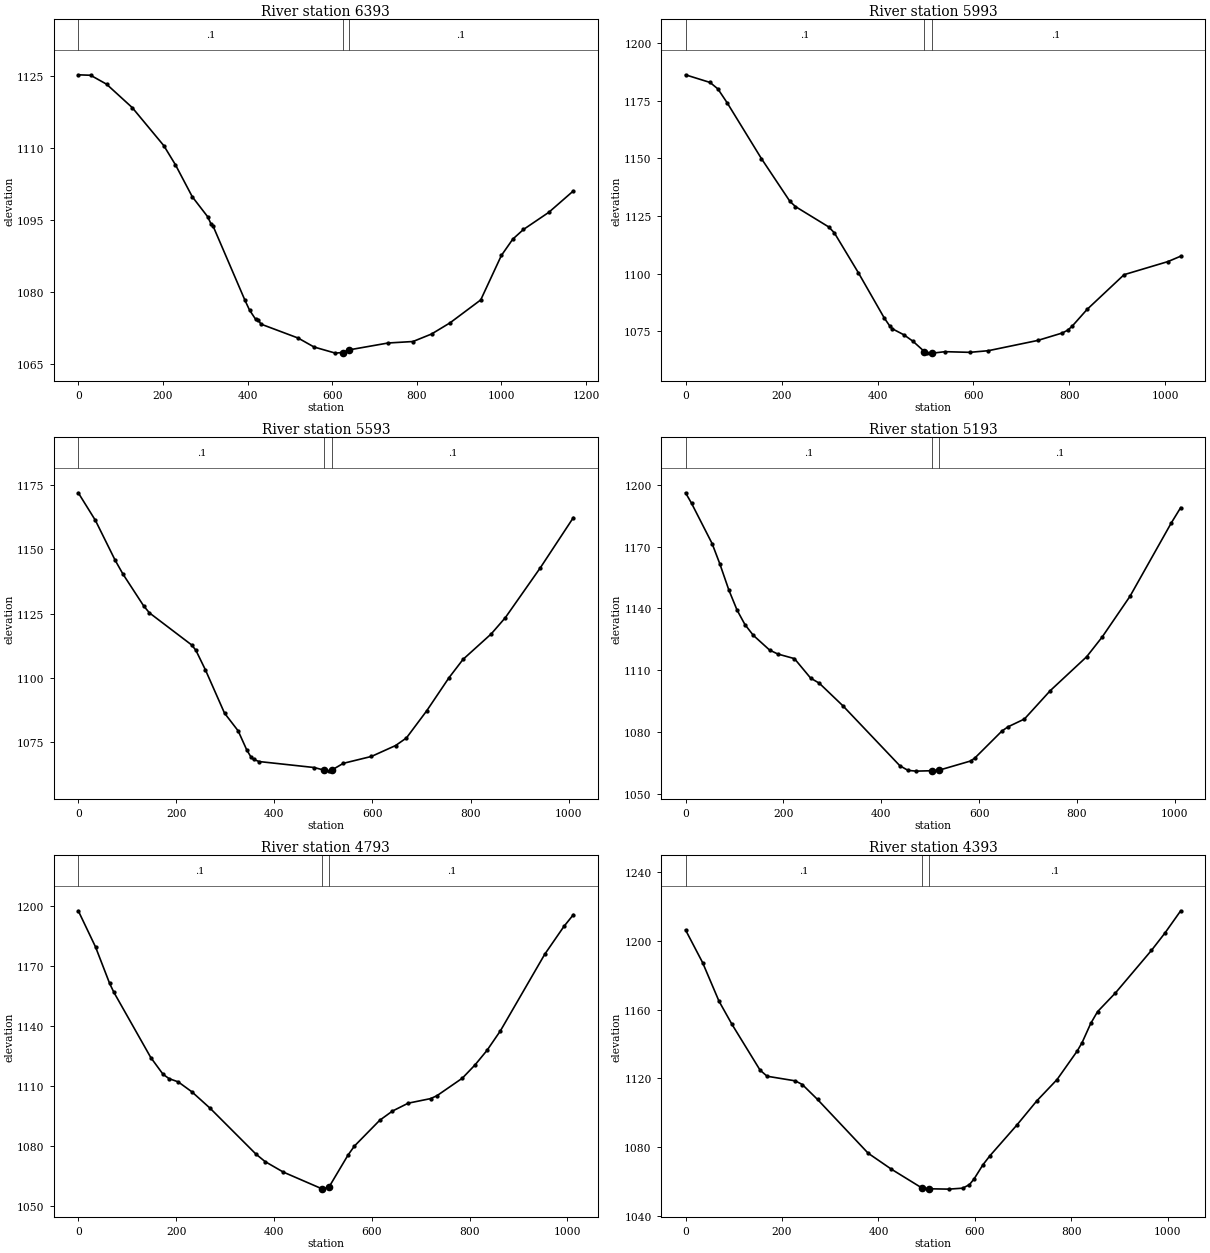
Type RM Length L Ch R = 1 ,6393,400.057,400,393.124
XS GIS Cut Line= 3
     1743020.337      235324.321     1743228.871      234727.677
     1743638.963      234379.276
#Sta/Elev= 30
       0 1125.23    29.1 1125.14    66.8 1123.28   127.6 1118.39   202.2 1110.46
   229.6 1106.48   269.4 1099.82   305.8 1095.65   314.0 1094.09   318.4 1093.74
   393.8 1078.26   404.7 1076.20   419.0 1074.30   425.8 1074.10   431.6 1073.28
   519.6 1070.37   557.3 1068.50   607.6 1067.23   624.5 1067.36   639.5 1067.90
   732.1 1069.34   791.0 1069.65   834.8 1071.21   878.4 1073.53   951.1 1078.32
   999.9 1087.58  1026.9 1090.99  1052.1 1093.00  1112.1 1096.58  1170.1 1101.04
#Mann= 3 , 0 , 0
       0     0.1       0   624.5   0.045       0   639.5     0.1       0
Bank Sta=   624.5,   639.5
Exp/Cntr=0.3,0.1

Type RM Length L Ch R = 1 ,5993,388.427,400,400.413
XS GIS Cut Line= 3
     1743505.317      235431.091     1743519.622      234926.003
     1743722.354      234440.139
#Sta/Elev= 30
       0 1186.20    51.1 1182.89    67.4 1180.08    86.8 1174.04   158.0 1149.92
   217.4 1131.38   229.1 1129.09   298.4 1120.27   310.0 1117.73   360.0 1100.47
   413.9 1080.88   425.5 1077.36   431.2 1076.11   455.0 1073.53   474.0 1070.72
   497.8 1066.25   502.5 1065.63   512.8 1065.60   515.0 1065.59   540.8 1066.22
   592.3 1065.93   630.9 1066.64   733.8 1071.08   785.3 1074.33   796.6 1075.56
   805.7 1077.27   836.7 1084.52   913.9 1099.59  1005.4 1105.27  1031.8 1107.60
#Mann= 3 , 0 , 0
       0     0.1       0   497.8   0.045       0   512.8     0.1       0
Bank Sta=   497.8,   512.8
Exp/Cntr=0.3,0.1

Type RM Length L Ch R = 1 ,5593,394.859,400,402.927
XS GIS Cut Line= 3
     1743614.174      235468.905     1743885.268      235037.508
     1744166.767      234624.094
#Sta/Elev= 30
       0 1171.90    34.9 1161.19    75.0 1145.77    91.0 1140.35   133.1 1128.03
   145.1 1125.25   231.2 1112.79   239.8 1110.73   259.3 1103.09   298.2 1086.30
   326.0 1079.42   343.4 1072.07   351.8 1069.36   357.4 1068.32   369.0 1067.49
   481.0 1065.17     502 1064.12   511.7 1063.77     517 1064.19   540.5 1066.80
   597.9 1069.48   647.2 1073.72   669.2 1076.66   710.5 1087.19   755.9 1100.04
   784.7 1107.20   842.1 1117.08   870.8 1123.37   942.6 1142.87  1009.7 1162.29
#Mann= 3 , 0 , 0
       0     0.1       0     502   0.045       0     517     0.1       0
Bank Sta=     502,     517
Exp/Cntr=0.3,0.1

Type RM Length L Ch R = 1 ,5193,395.061,400,391.417
XS GIS Cut Line= 3
     1743818.735      235656.810     1744176.877      235292.294
     1744505.766      234914.479
#Sta/Elev= 30
       0 1196.11    12.2 1191.04    54.2 1171.48    70.0 1161.62    88.5 1148.87
   105.2 1139.16   121.3 1132.12   138.4 1126.89   171.7 1119.73   188.6 1117.79
   222.5 1115.56   255.7 1106.07   273.3 1103.62   321.5 1092.66   438.0 1063.51
   454.7 1061.26   471.3 1060.90   503.5 1061.10   518.5 1061.38   582.8 1065.84
   591.7 1067.37   646.6 1080.38   659.0 1082.42   692.6 1086.22   745.5 1100.03
   819.8 1116.48   851.3 1126.00   908.2 1145.79   992.9 1181.55  1011.9 1188.92
#Mann= 3 , 0 , 0
       0     0.1       0   503.5   0.045       0   518.5     0.1       0
Bank Sta=   503.5,   518.5
Exp/Cntr=0.3,0.1

Type RM Length L Ch R = 1 ,4793,364.823,400,365.949
XS GIS Cut Line= 3
     1744306.402      235983.119     1744470.632      235505.039
     1744675.317      235041.650
#Sta/Elev= 30
       0 1197.74    35.2 1179.68    64.1 1161.37    72.8 1156.92   148.2 1124.29
   173.3 1115.90   185.6 1113.74   204.3 1112.11   232.3 1107.12   269.7 1098.86
   363.1 1075.98   381.8 1072.23   419.2 1066.95     498 1058.60   499.7 1058.43
     513 1059.67   551.4 1075.48   564.4 1079.97   616.3 1092.92   642.2 1097.50
   674.4 1101.45   720.1 1103.74   733.1 1105.18   785.0 1113.95   811.0 1120.60
   835.4 1127.85   862.9 1137.67   953.7 1176.06   992.7 1189.91  1012.1 1195.82
#Mann= 3 , 0 , 0
       0     0.1       0     498   0.045       0     513     0.1       0
Bank Sta=     498,     513
Exp/Cntr=0.3,0.1

Type RM Length L Ch R = 1 ,4393,384.948,400,390.062
XS GIS Cut Line= 3
     1744466.474      236087.260     1744756.240      235682.893
     1745035.690      235233.626
#Sta/Elev= 30
       0 1206.29    35.3 1187.35    69.3 1164.92    96.0 1151.54   154.4 1124.85
   169.0 1121.27   227.5 1118.58   242.1 1116.44   273.6 1107.78   378.6 1076.51
   426.7 1067.24     490 1056.31     505 1055.83   546.2 1055.63   574.6 1056.19
   588.6 1058.23   598.2 1061.54   616.5 1069.74   630.5 1074.83   686.4 1092.70
   728.4 1106.98   770.3 1119.34   812.3 1136.02   822.3 1140.88   840.2 1152.00
   854.2 1158.79   891.3 1169.68   966.1 1194.46   994.0 1204.53  1026.6 1217.44
#Mann= 3 , 0 , 0
       0     0.1       0     490   0.045       0     505     0.1       0
Bank Sta=     490,     505
Exp/Cntr=0.3,0.1

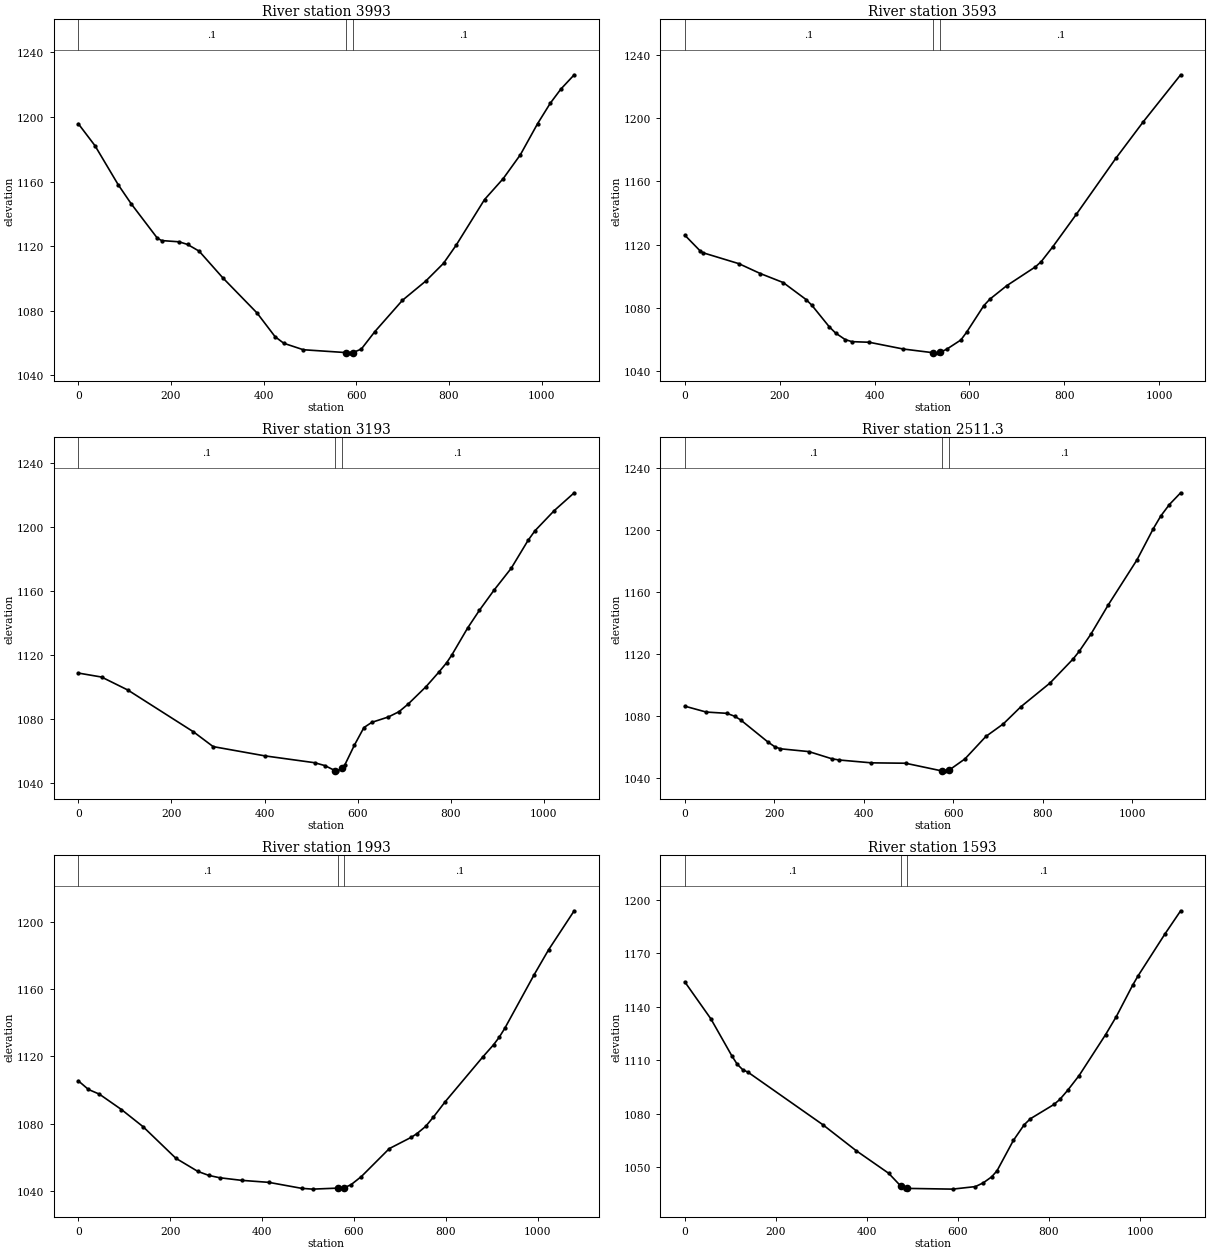
Type RM Length L Ch R = 1 ,3993,404.607,400,392.407
XS GIS Cut Line= 3
     1744826.925      236304.629     1745008.155      235748.884
     1745177.573      235293.724
#Sta/Elev= 30
       0 1195.80    36.0 1182.19    85.9 1158.10   113.9 1146.29   170.4 1124.96
   179.8 1123.42   217.5 1122.65   235.8 1121.01   260.8 1116.85   311.7 1100.37
   385.7 1078.56   424.7 1063.85   443.5 1059.77   485.6 1055.77     577 1054.02
   585.5 1053.67     592 1053.91   610.8 1056.19   640.2 1067.07   699.5 1086.39
   750.2 1098.41   788.2 1109.31   815.6 1120.60   876.8 1148.85   917.1 1161.82
   954.1 1176.60   991.3 1195.88  1018.7 1208.54  1041.5 1217.29  1070.2 1226.12
#Mann= 3 , 0 , 0
       0     0.1       0     577   0.045       0     592     0.1       0
Bank Sta=     577,     592
Exp/Cntr=0.3,0.1

Type RM Length L Ch R = 1 ,3593,361.625,400,402.099
XS GIS Cut Line= 3
     1745173.580      236403.055     1745270.331      235881.467
     1745369.200      235376.508
#Sta/Elev= 30
       0 1125.96    32.5 1115.94    38.3 1114.81   114.0 1107.89   159.1 1101.65
   207.4 1095.93   255.7 1085.14   267.7 1081.58   304.0 1068.07   317.7 1063.96
   338.1 1059.78   352.3 1058.48   388.5 1058.10   460.3 1053.82     523 1051.48
   533.4 1051.21     538 1051.72   551.8 1053.66   581.8 1059.53   593.9 1064.43
   630.2 1081.30   642.9 1085.40   678.6 1093.96   739.1 1105.91   751.2 1109.19
   775.4 1118.52   825.0 1139.10   908.4 1174.63   966.6 1197.93  1045.0 1227.55
#Mann= 3 , 0 , 0
       0     0.1       0     523   0.045       0     538     0.1       0
Bank Sta=     523,     538
Exp/Cntr=0.3,0.1

Type RM Length L Ch R = 1 ,3193,658.399,681.698,679.811
XS GIS Cut Line= 3
     1745255.926      236431.110     1745557.519      235960.744
     1745851.664      235548.646
#Sta/Elev= 30
       0 1108.68    49.9 1106.19   106.3 1098.08   247.3 1071.96   289.6 1062.72
   400.6 1056.94   507.7 1052.65   529.7 1050.84   551.3 1047.74   555.3 1047.40
   566.3 1049.22   572.7 1051.42   593.1 1063.67   613.5 1074.63   630.5 1077.89
   666.0 1081.24   688.8 1084.53   708.5 1089.30   747.2 1100.27   774.7 1109.35
   790.9 1115.03   802.2 1119.91   836.2 1136.80   861.7 1147.95   893.0 1160.50
   929.8 1174.12   966.0 1191.56   980.9 1197.59  1022.2 1210.16  1065.1 1221.30
#Mann= 3 , 0 , 0
       0     0.1       0   551.3   0.045       0   566.3     0.1       0
Bank Sta=   551.3,   566.3
Exp/Cntr=0.3,0.1

Type RM Length L Ch R = 1 ,2511.3,497.713,518.302,501.605
XS GIS Cut Line= 3
     1745715.189      236671.747     1745935.336      236098.644
     1746140.336      235648.483
#Sta/Elev= 30
       0 1086.22    47.8 1082.42    93.8 1081.60   111.6 1079.70   124.7 1077.38
   185.6 1063.14   201.0 1060.04   213.7 1058.70   277.5 1056.88   328.2 1052.30
   344.3 1051.48   417.2 1049.62   493.5 1049.37     575 1044.39   582.5 1044.27
     590 1044.72   626.4 1052.16   673.1 1066.65   712.2 1074.78   751.3 1085.81
   816.6 1101.17   868.4 1116.75   881.8 1121.60   907.9 1132.68   947.0 1151.71
  1010.9 1180.63  1047.7 1200.92  1064.4 1209.09  1083.5 1216.43  1108.6 1223.98
#Mann= 3 , 0 , 0
       0     0.1       0     575   0.045       0     590     0.1       0
Bank Sta=     575,     590
Exp/Cntr=0.3,0.1

Type RM Length L Ch R = 1 ,1993,426.194,400,340.604
XS GIS Cut Line= 3
     1746213.044      236814.688     1746250.292      236244.200
     1746306.789      235740.089
#Sta/Elev= 30
       0 1105.54    21.9 1100.44    45.7 1097.66    93.9 1088.51   140.9 1078.35
   212.3 1059.62   259.9 1051.87   283.7 1049.49   307.5 1048.09   355.1 1046.55
   414.6 1045.35   485.9 1041.81   509.7 1041.34   564.2 1041.93   579.2 1042.27
   593.1 1043.89   616.0 1048.82   676.7 1065.36   724.5 1072.06   736.5 1074.17
   755.6 1078.47   772.3 1083.92   798.6 1093.24   879.8 1119.58   903.7 1126.96
   915.7 1131.31   927.8 1136.57   992.0 1168.49  1023.2 1183.17  1079.0 1206.33
#Mann= 3 , 0 , 0
       0     0.1       0   564.2   0.045       0   579.2     0.1       0
Bank Sta=   564.2,   579.2
Exp/Cntr=0.3,0.1

Type RM Length L Ch R = 1 ,1593,404.196,400,425.492
XS GIS Cut Line= 3
     1746526.757      236896.086     1746542.507      236414.963
     1746591.006      235809.120
#Sta/Elev= 30
       0 1154.01    57.2 1133.27   103.3 1112.46   115.2 1107.71   127.1 1104.69
   139.0 1103.22   302.8 1073.82   376.5 1059.14   447.8 1046.45   473.9 1039.40
   483.5 1037.87   488.9 1037.94   588.1 1037.53   638.3 1038.95   655.6 1041.05
   674.0 1044.42   685.9 1047.85   721.7 1064.87   745.5 1073.70   759.2 1077.09
   811.0 1085.13   823.9 1087.96   840.8 1092.99   866.2 1101.37   924.2 1124.30
   948.0 1134.55   983.7 1152.10   995.6 1157.36  1055.2 1181.12  1089.2 1193.95
#Mann= 3 , 0 , 0
       0     0.1       0   473.9   0.045       0   488.9     0.1       0
Bank Sta=   473.9,   488.9
Exp/Cntr=0.3,0.1

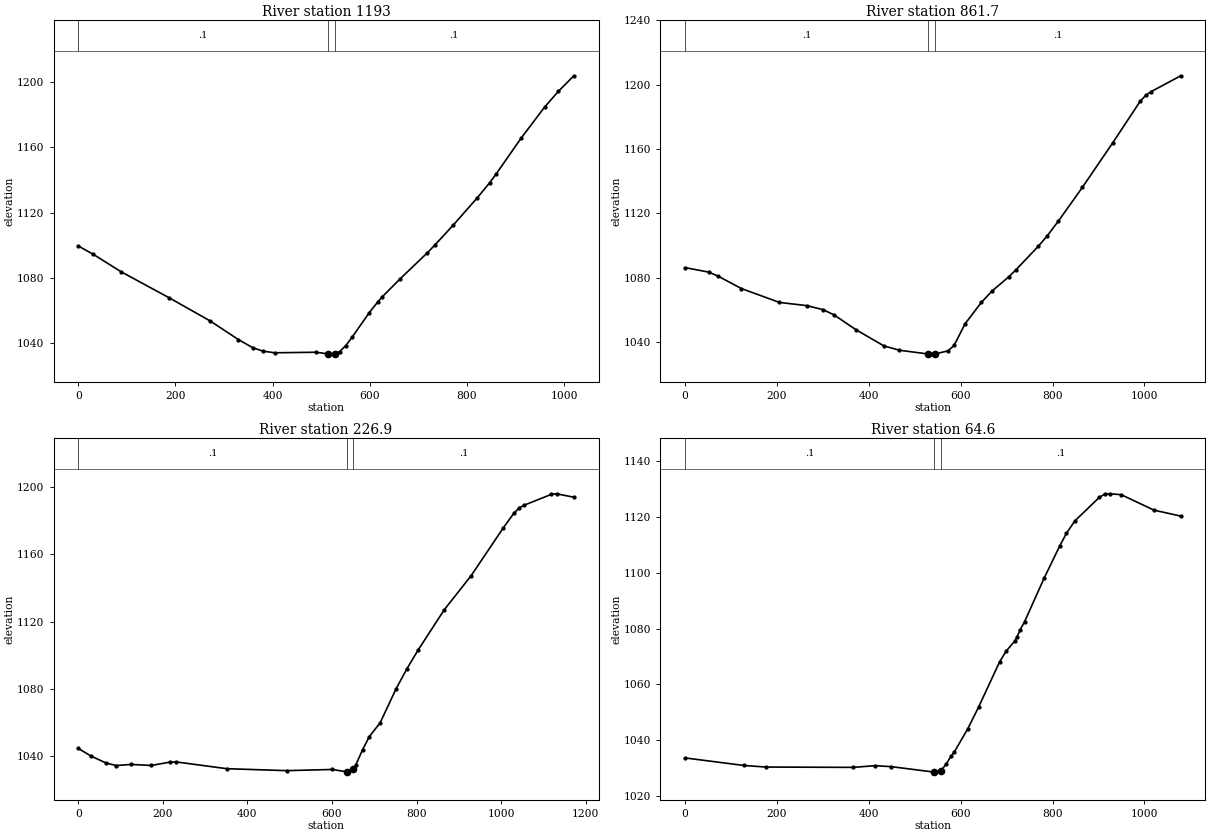
Type RM Length L Ch R = 1 ,1193,321.997,331.219,322.502
XS GIS Cut Line= 3
     1746980.346      236750.983     1746886.808      236238.985
     1746693.993      235778.117
#Sta/Elev= 30
       0 1099.52    29.9 1094.59    88.1 1083.75   186.8 1067.87   271.3 1053.68
   329.5 1042.26   359.1 1037.28   379.9 1035.20   404.0 1034.17   488.5 1034.50
     513 1033.57   516.7 1033.35     528 1033.69   537.9 1034.94   550.8 1038.62
   563.6 1043.69   598.8 1058.66   617.0 1065.50   626.0 1068.52   662.3 1079.37
   718.1 1095.23   734.9 1100.40   771.2 1112.09   821.0 1128.90   846.8 1138.22
   859.6 1143.35   911.1 1165.32   959.8 1184.50   988.3 1194.14  1020.0 1203.66
#Mann= 3 , 0 , 0
       0     0.1       0     513   0.045       0     528     0.1       0
Bank Sta=     513,     528
Exp/Cntr=0.3,0.1

Type RM Length L Ch R = 1 ,861.7,400.696,634.797,507.61
XS GIS Cut Line= 3
     1747152.443      236784.413     1747159.636      236263.165
     1747108.290      235707.995
#Sta/Elev= 30
       0 1086.17    51.0 1083.40    71.6 1080.88   122.2 1073.18   205.3 1064.52
   264.7 1062.54   300.3 1060.03   324.1 1056.76   371.6 1047.61   432.8 1037.45
   466.6 1034.77   529.6 1032.43   537.9 1032.36   544.6 1032.55   572.1 1034.36
   585.6 1037.82   609.4 1051.20   645.2 1064.65   669.0 1071.83   704.8 1080.49
   720.1 1084.80   768.5 1099.33   788.3 1105.95   812.2 1114.96   864.6 1136.02
   931.3 1163.97   991.0 1189.78  1002.9 1193.36  1014.8 1195.69  1078.8 1205.49
#Mann= 3 , 0 , 0
       0     0.1       0   529.6   0.045       0   544.6     0.1       0
Bank Sta=   529.6,   544.6
Exp/Cntr=0.3,0.1

Type RM Length L Ch R = 1 ,226.9,326.756,162.384,168.342
XS GIS Cut Line= 3
     1747425.462      236644.539     1747461.558      236031.133
     1747268.556      235508.065
#Sta/Elev= 30
       0 1044.60    29.9 1040.09    65.2 1035.98    89.3 1034.43   125.0 1035.09
   172.6 1034.47   216.9 1036.48   232.1 1036.56   351.0 1032.56   492.6 1031.39
   600.7 1032.09   635.3 1030.68   637.9 1030.51   650.3 1032.31   656.4 1034.77
   672.5 1043.90   688.4 1051.66   713.8 1059.80   751.7 1080.09   777.0 1091.89
   804.3 1103.33   865.6 1127.09   928.9 1147.25  1004.8 1175.63  1030.1 1184.45
  1042.8 1187.60  1055.4 1189.36  1118.9 1195.72  1131.4 1196.04  1172.0 1194.05
#Mann= 3 , 0 , 0
       0     0.1       0   635.3   0.045       0   650.3     0.1       0
Bank Sta=   635.3,   650.3
Exp/Cntr=0.3,0.1

Type RM Length L Ch R = 1 ,64.6,43.381,64.55,85.315
XS GIS Cut Line= 3
     1747589.405      236493.613     1747596.597      235972.364
     1747545.252      235417.194
#Sta/Elev= 30
       0 1033.68   128.2 1030.98   175.7 1030.42   365.7 1030.30   413.9 1030.91
   448.8 1030.56   541.8 1028.62   543.9 1028.60   556.8 1029.16   567.8 1031.35
   579.7 1034.54   586.4 1035.92   615.4 1044.15   639.3 1052.04   684.6 1068.08
   698.9 1071.92   717.3 1075.47   722.8 1077.13   729.3 1079.56   739.2 1082.53
   781.8 1098.14   815.6 1109.61   830.1 1114.11   848.3 1118.53   901.6 1126.96
   913.2 1128.13   925.5 1128.25   949.3 1127.95  1020.8 1122.41  1078.8 1120.28
#Mann= 3 , 0 , 0
       0     0.1       0   541.8   0.045       0   556.8     0.1       0
Bank Sta=   541.8,   556.8
Exp/Cntr=0.3,0.1